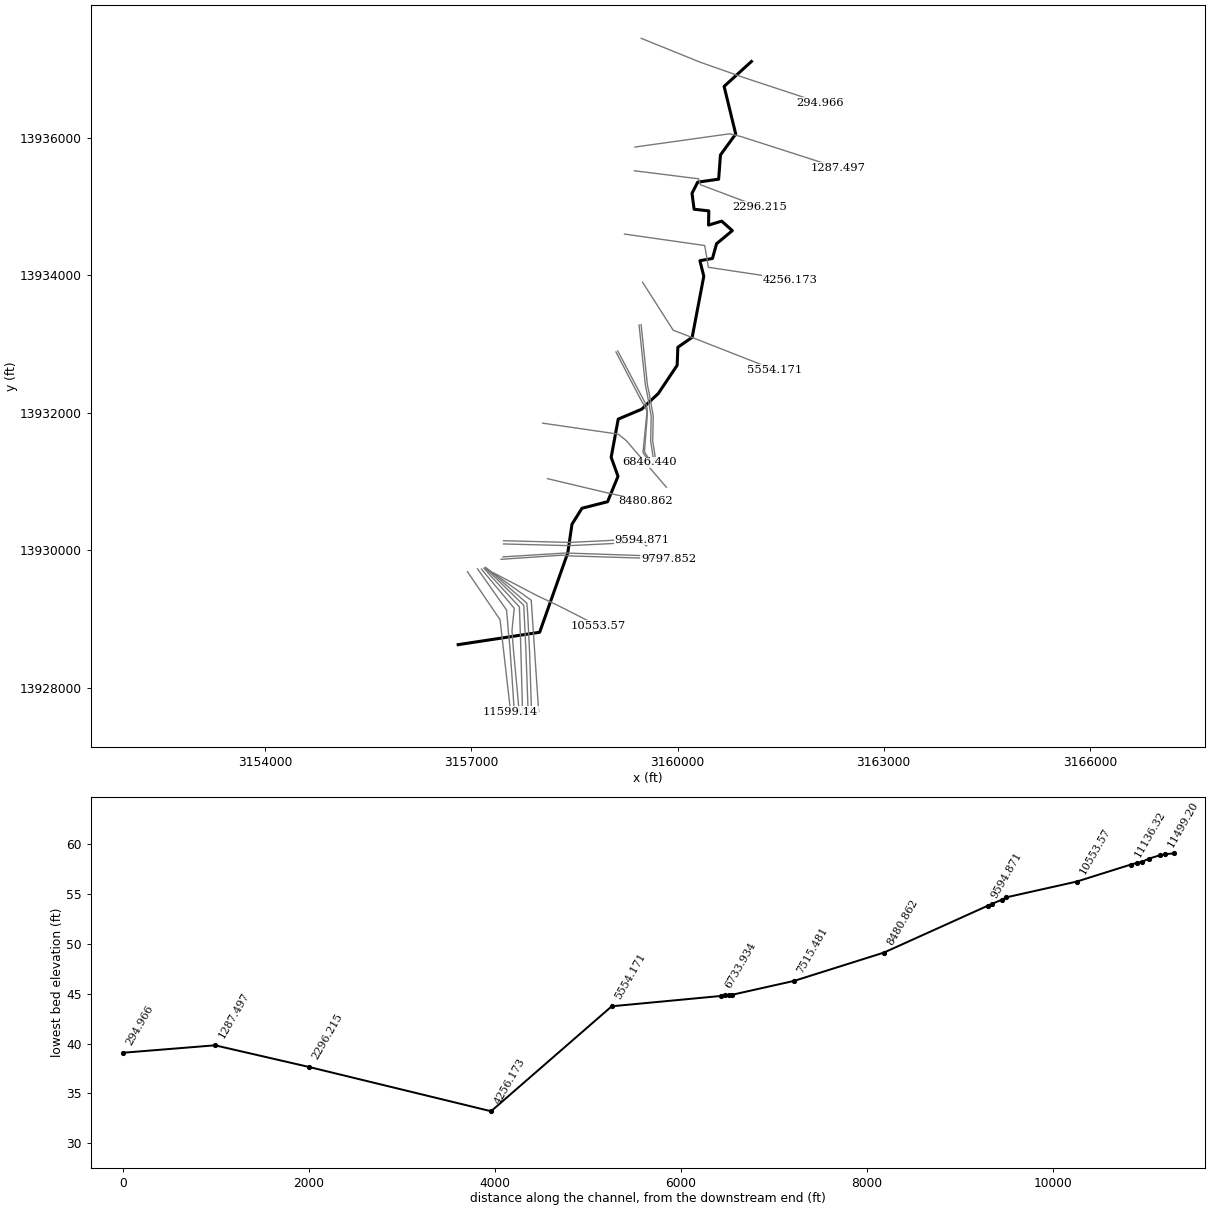
--- G103-43-00.prj (project) ---

Proj Title=G103-43-00
Current Plan=p05
Default Exp/Contr=.3,.1
English Units
Geom File=g02
Flow File=f01
Flow File=f03
Plan File=p04
Plan File=p05
Y Axis Title=Elevation
X Axis Title(PF)=Main Channel Distance
X Axis Title(XS)=Station
BEGIN DESCRIPTION:
San Jacinto River Watershed
Jordan Gully
HCFCD Unit G103-43-00
(Flood Hazard) Model
10, 2, 1, 0.2% Event
Filename g1034300.prj
Prepared by:  FTN Associates Ltd.   DATE:  May 2003
Reviewed by: 	 DATE:
STATUS (FINAL RAS)
The slope for normal depth downstream calculations was determined to be 0.000887.  This number was calculated by using the following river stations (5554.171 and 294.966).
Adjusted Manning's "n" values based on FIS Data from Sept. 1987.
END DESCRIPTION:
DSS File=dss
DSS Export Rating Curves= 0
DSS Export Rating Curve Sorted= 0
DSS Export Volume Flow Curves= 0
DXF OffsetX= 0
DXF OffsetY= 0
DXF ScaleX= 1
DXF ScaleY= 10

--- G103-43-00.p05 (plan) ---

Plan Title=Floodway
Version=Version 3.0.1  Mar 2001
Short Identifier=Floodway0607
Geom File=g02
Flow File=f03
Subcritical Flow
K Sum by GR= 0
Std Step Tol= 0.01
Critical Tol= 0.01
Num of Std Step Trials= 20
Max Error Tol= 0.3
Flow Tol Ratio= 0.001
Split Flow NTrial= 30
Split Flow Tol= 0.02
Split Flow Ratio= 0.02
Log Output Level= 0
Friction Slope Method= 1
Unsteady Friction Slope Method= 2
Parabolic Critical Depth
Global Vel Dist= 0 , 0 , 0
Global Log Level= 0
CheckData=True
Encroach Param=-1 ,0,0, 2
Encroach River=G103-43-00
Encroach Reach=Jordan Gully
Encroach Node=11599.14
       1     900    1250
Encroach Node=11499.20
       1     955    1305
Encroach Node=11473.2
       1     955    1305
Encroach Node=11447.17
       1     955    1305
Encroach Node=11329.01
       1    1010    1330
Encroach Node=11259.25
       1    1080    1380
Encroach Node=11233.02
       1    1080    1380
Encroach Node=11206.79
       1    1080    1380
Encroach Node=11136.32
       1    1140    1440
Encroach Node=10553.57
       1     825    1125
Encroach Node=9797.852
       1  905.31     990
Encroach Node=9753.782
       1  894.33  977.33
Encroach Node=9697.84
       1  894.33  977.33
Encroach Node=9641.901
       1     895     977
Encroach Node=9594.871
       1     891     980
Encroach Node=8480.862
       1     834    1016
Encroach Node=7515.481
       1     967  1095.2
Encroach Node=6846.440
       1     840     960
Encroach Node=6815.437
       1 1089.71 1207.45
Encroach Node=6793.145
       1 1089.71 1207.45
Encroach Node=6770.853
       1    1090 1207.45
Encroach Node=6733.934
       1    1071 1188.61
Encroach Node=5554.171
       1     973 1143.19
Encroach Node=4256.173
       1 1352.45    1507
Encroach Node=2296.215
       1     620    1170
Encroach Node=1287.497
       1 1388.34 1848.84
Encroach Node=294.966
       1  582.46  859.98
Encroach Reach=G103-43-00_0003
Encroach Node=11599.14
       1     900    1250
Encroach Node=11499.20
       1     955    1305
Encroach Node=11473.2
       1     955    1305
Encroach Node=11447.17
       1     955    1305
Encroach Node=11329.01
       1    1010    1330
Encroach Node=11259.25
       1    1080    1380
Encroach Node=11233.02
       1    1080    1380
Encroach Node=11206.79
       1    1080    1380
Encroach Node=11136.32
       1    1140    1440
Encroach Node=10553.57
       1     825    1125
Encroach Node=9797.852
       1  905.31     990
Encroach Node=9753.782
       1  894.33  977.33
Encroach Node=9697.84
       1  894.33  977.33
Encroach Node=9641.901
       1     895     977
Encroach Node=9594.871
       1     891     980
Encroach Node=8480.862
       1     834    1016
Encroach Node=7515.481
       1     967  1095.2
Encroach Node=6846.440
       1     840     960
Encroach Node=6815.437
       1 1089.71 1207.45
Encroach Node=6793.145
       1 1089.71 1207.45
Encroach Node=6770.853
       1    1090 1207.45
Encroach Node=6733.934
       1    1071 1188.61
Encroach Node=5554.171
       1     973 1143.19
Encroach Node=4256.173
       1 1352.45    1507
Encroach Node=2296.215
       1     620    1170
Encroach Node=1287.497
       1 1388.34 1848.84
Encroach Node=294.966
       1  582.46  859.98
Computation Interval=1HOUR
Output Interval=1HOUR
Run HTab= 0
Run UNet= 0
Run PostProcess= 0
UNET Theta= 1
UNET ZTol= 0.02
UNET ZSATol= 0.1
UNET MxIter= 20
UNET MaxInSteps= 20
UNET DtIC= 0
UNET DtMin= 0
UNET MaxCRTS= 20
UNET WFStab= 2
UNET SFStab= 1
UNET WFX= 1
UNET SFX= 1
UNET Convert EG Bridges=-1
UNET Use Existing IB Tables=-1
Instantaneous Interval=1HOUR
Write IC File= 0
Write Velocity= 0
Write Detailed= 0

--- G103-43-00.p04 (plan) ---

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Plan Title=FEMA Effective June 2007
Short Identifier=FEMAeff0607
Geom File=g02
Flow File=f01
Encroach Param=-1 ,0,0, 0

--- G103-43-00.f03 (steady flow) ---

Flow Title=Floodway
Version=Version 3.0.1  Mar 2001
Number of Profiles= 2
Profile Names=1PCT_100yr, 1PCTFloodway_100yrFW
River Rch & RM=G103-43-00,G103-43-00_0003    ,11599.14
    2073    2073
River Rch & RM=G103-43-00,G103-43-00_0003    ,10553.57
    2124    2124
River Rch & RM=G103-43-00,G103-43-00_0003    ,9594.871
    2184    2184
River Rch & RM=G103-43-00,G103-43-00_0003    ,8480.862
    2688    2688
River Rch & RM=G103-43-00,G103-43-00_0003    ,6770.853
    2783    2783
River Rch & RM=G103-43-00,G103-43-00_0003    ,4256.173
    2900    2900
River Rch & RM=G103-43-00,G103-43-00_0003    ,1287.497
    2940    2940
Boundary for River Rch & Prof#=G103-43-00,G103-43-00_0003    , 1
Up Type= 0
Dn Type= 3
Dn Slope=.000887
Boundary for River Rch & Prof#=G103-43-00,G103-43-00_0003    , 2
Up Type= 0
Dn Type= 3
Dn Slope=.000887
DSS Import GetInterval= 0
DSS Import GetPeak= 0
DSS Import FillOption= 0

--- G103-43-00.f01 (steady flow) ---

Flow Title=FEMA Effective June 2007
Version=Version 3.0.1  Mar 2001
Number of Profiles= 4
Profile Names=10PCT_10yr, 2PCT_50yr, 1PCT_100yr, 0.2PCT_500yr
River Rch & RM=G103-43-00,G103-43-00_0003    ,11599.14
    1327    1813    2073    2775
River Rch & RM=G103-43-00,G103-43-00_0003    ,10553.57
    1368    1856    2124    2852
River Rch & RM=G103-43-00,G103-43-00_0003    ,9594.871
    1418    1908    2184    2944
River Rch & RM=G103-43-00,G103-43-00_0003    ,8480.862
    1707    2339    2688    3667
River Rch & RM=G103-43-00,G103-43-00_0003    ,6770.853
    1735    2417    2783    3836
River Rch & RM=G103-43-00,G103-43-00_0003    ,4256.173
    1770    2513    2900    4046
River Rch & RM=G103-43-00,G103-43-00_0003    ,1287.497
    1782    2546    2940    4118
Boundary for River Rch & Prof#=G103-43-00,G103-43-00_0003    , 1
Up Type= 0
Dn Type= 3
Dn Slope=.000887
Boundary for River Rch & Prof#=G103-43-00,G103-43-00_0003    , 2
Up Type= 0
Dn Type= 3
Dn Slope=.000887
DSS Import GetInterval= 0
DSS Import GetPeak= 0
DSS Import FillOption= 0

--- G103-43-00.g02 (geometry) ---

Geom Title=G103-43-00 June 2007
Version=Version 3.0.1  Mar 2001

River Reach=G103-43-00      ,G103-43-00_0003
Reach XY= 30
     3156808.929    13928628.487     3157994.487    13928808.712
     3158403.634    13929964.548     3158464.919    13930380.758
     3158609.896    13930612.825      3158982.52    13930707.834
      3159134.27    13931077.061     3159034.896    13931354.182
     3159137.531    13931909.904      3159476.93     13932053.07
     3159720.926    13932282.811     3159995.111    13932693.205
     3160004.984    13932955.143     3160213.381    13933099.996
      3160382.56    13933988.646     3160325.972    13934214.848
     3160508.464    13934247.057     3160568.226    13934461.432
     3160798.064    13934652.309       3160642.5    13934790.166
     3160451.633    13934732.491     3160455.183    13934939.426
     3160241.198    13934963.381      3160211.14    13935194.924
     3160293.794    13935357.481     3160598.458    13935400.547
     3160625.075    13935753.039     3160846.762    13936057.913
     3160678.135    13936750.548     3161075.842    13937113.329

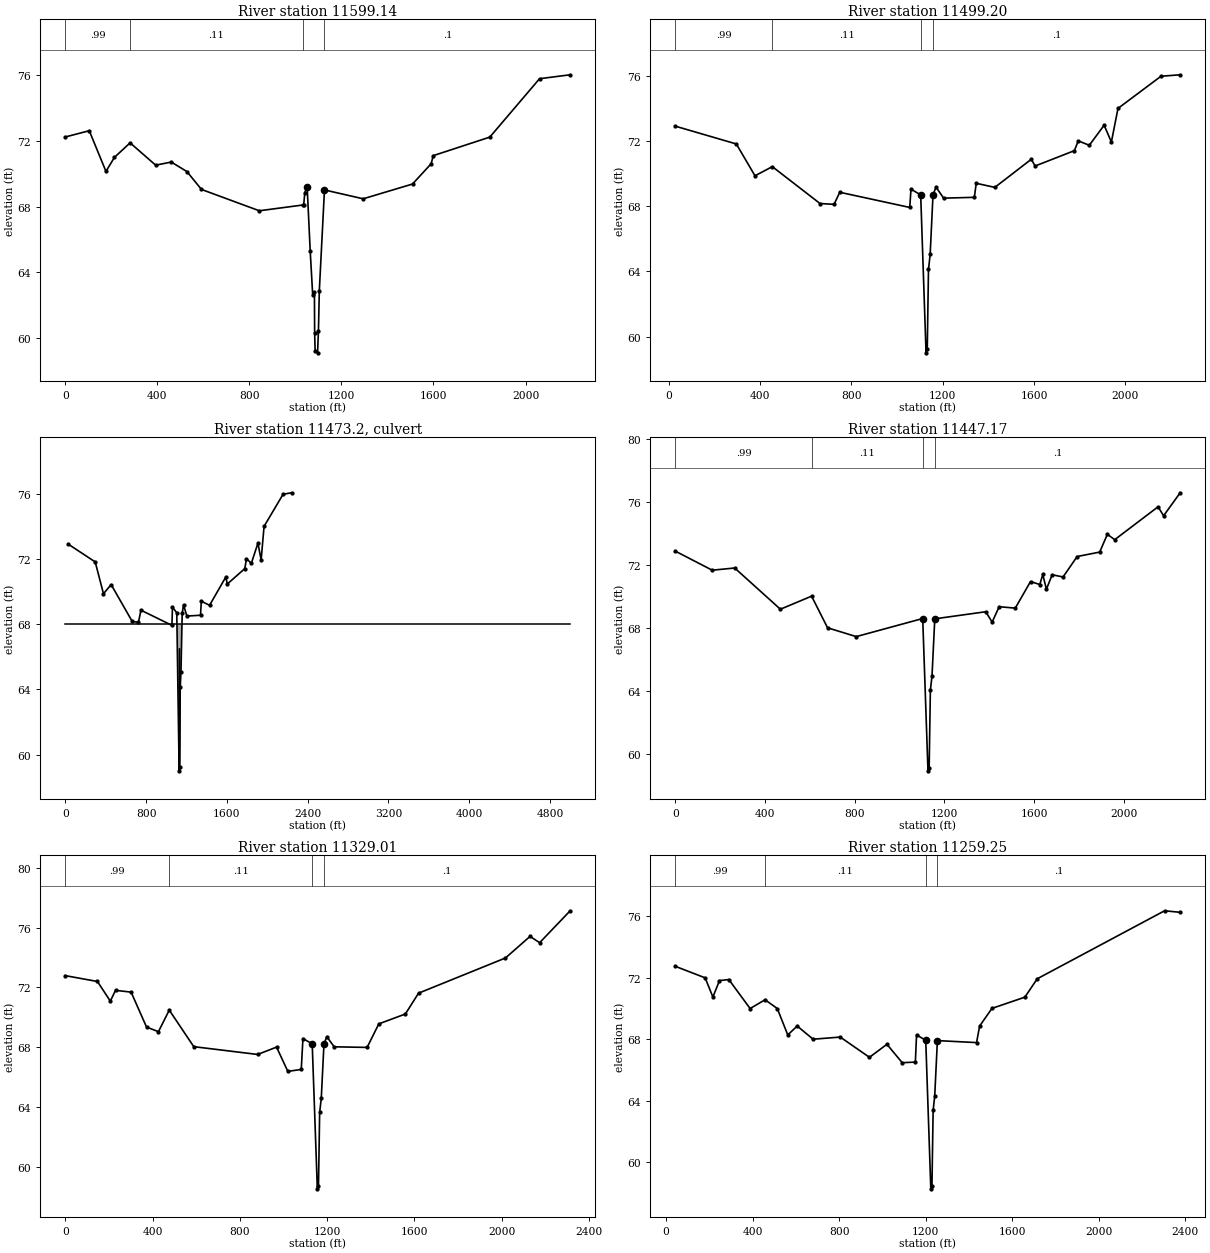
Type RM Length L Ch R = 1 ,11599.14,106.41,99.95,99.5
BEGIN DESCRIPTION:
Copy of 421s2u; XS 4/4.
Bank Station Offset = 3949
END DESCRIPTION:
XS GIS Cut Line= 3
     3156945.019    13929688.866     3157418.085    13928991.095
     3157571.831    13927648.773
#Sta/Elev= 30
       0   72.25  103.98   72.63  176.47   70.15  213.63   71.01  281.46   71.89
  392.53   70.53  460.53   70.72  528.37   70.14  591.71   69.05  843.02   67.75
 1031.23    68.1 1035.99   68.12 1040.74   68.86    1051    69.2 1064.18   65.31
 1075.15   62.59 1082.51   62.78 1083.47    60.3  1085.7    59.2 1096.24   59.09
 1100.06   60.45 1103.84   62.88  1126.2   69.02 1294.45   68.48 1508.86   69.38
 1590.14   70.62  1598.8   71.11 1844.78   72.24 2060.94    75.8 2194.11   76.04
#Mann= 4 ,-1 , 0
       0     .99       0  281.46     .11       0 1031.23     .05       0
  1126.2      .1       0
Bank Sta=1051,1126.2
XS Rating Curve= 0
Exp/Cntr=.5,.3

Type RM Length L Ch R = 1 ,11499.20,79.61,52.03,49.41
BEGIN DESCRIPTION:
XS 3/4;
Channel geometry adjusted for slope and width
xs shifted 28.55' to the right to allow encroachment setting
END DESCRIPTION:
XS GIS Cut Line= 6
      3157089.63    13929733.058     3157513.172    13929132.072
     3157541.305    13928795.828     3157559.313    13928618.152
     3157591.479    13928169.058     3157624.576    13927659.656
#Sta/Elev= 30
   28.55    72.9  295.81   71.81  377.54   69.86  453.48   70.42  662.49   68.16
  724.11   68.11  748.99   68.85 1055.64   67.92 1061.07   69.04 1103.59   68.69
  1127.1   59.01 1132.36   59.22 1137.75   64.12 1145.09   65.04 1157.46   68.67
 1170.55   69.17 1204.08   68.49 1338.66   68.54 1346.95    69.4 1428.46   69.15
 1587.98   70.87 1605.16   70.46 1777.11    71.4 1793.92      72 1842.43   71.73
 1907.42   72.96 1939.12   71.93 1968.13   73.99 2156.52   75.96 2240.56   76.05
#Mann= 4 ,-1 , 0
   28.55     .99       0  453.48     .11       0 1103.59     .06       0
 1157.46      .1       0
#XS Ineff= 2 , 0
   28.55 1103.59      68 1157.46   28.55      68
Permanent Ineff=
       F       F
Bank Sta=1103.59,1157.46
XS Rating Curve= 0
Exp/Cntr=.5,.3

Type RM Length L Ch R = 2 ,11473.2 ,,,
BEGIN DESCRIPTION:
(424s5)    Access Road
New Culvert added to geometry per PMT request
END DESCRIPTION:
Bridge Culvert--1,0,-1,-1, 0
Deck Dist Width WeirC Skew NumUp NumDn MinLoCord MaxHiCord MaxSubmerge Is_Ogee
18.015,16,2.6,0, 2, 2, , , .95, 0, 0,0,,
       0    5000
      68      68
                
       0    5000
      68      68
                
BR Coef=-1 , 0 , 0 ,, 0 ,,,.8,0,,0,
WSPro=,,,, 1 ,,,, 0 ,,,, 0 ,,,,-1 ,-1 ,-1 , 0 , 0 , 0 , 0 , 0
Culvert=1,7.5,,30,.03,.9,1,2,3,59,1130.53,59,1130.53,Culvert #1  , 0 ,11.015
Culvert Bottom n=.03
BC Design=,, 0 ,, 0 ,,,,,,

Type RM Length L Ch R = 1 ,11447.17,101.97,118.16,114.95
BEGIN DESCRIPTION:
XS 2/4;
Channel geometry adjusted for slope and width
END DESCRIPTION:
XS GIS Cut Line= 6
      3157148.09    13929728.561     3157210.643    13929651.052
     3157624.756    13929157.463     3157591.727    13928834.244
     3157610.935    13928577.335     3157696.705    13927655.519
#Sta/Elev= 30
       0   72.86  164.57   71.65  264.79   71.79  468.69   69.17  607.88      70
  679.08   67.99  807.09   67.43 1103.59   68.58  1127.1    58.9 1132.36   59.11
 1137.75   64.01 1145.09   64.93 1157.46   68.56 1384.66   69.01 1413.34   68.35
 1444.61   69.33 1516.66   69.24  1584.6   70.93 1625.94   70.74 1639.31   71.38
 1655.43   70.44 1681.07   71.36  1729.7   71.22  1792.6   72.52 1893.09    72.8
 1927.43   73.93 1960.21   73.59 2153.63   75.68 2178.27   75.11 2252.22   76.57
#Mann= 4 ,-1 , 0
       0     .99       0  607.88     .11       0 1103.59     .06       0
 1157.46      .1       0
#XS Ineff= 2 , 0
       0 1103.59      68 1157.46       0      68
Permanent Ineff=
       F       F
Bank Sta=1103.59,1157.46
XS Rating Curve= 0
Exp/Cntr=.5,.3

Type RM Length L Ch R = 1 ,11329.01,67.69,69.76,72.03
BEGIN DESCRIPTION:
XS 1/4 and XS 4/4;
Channel geometry adjusted for slope and width
END DESCRIPTION:
XS GIS Cut Line= 5
      3157184.06    13929742.051     3157258.864    13929654.531
     3157699.945    13929177.329     3157717.212    13928673.156
      3157746.17    13927628.538
#Sta/Elev= 30
       0   72.79  147.12    72.4   206.2   71.09  230.15   71.81   301.5   71.69
  372.14   69.36  426.78   69.05   476.4   70.49  588.79   68.05  881.56   67.53
  968.34   68.02 1019.99    66.4 1081.57   66.53 1089.24   68.59 1131.76   68.24
 1155.27   58.56 1160.53   58.77 1165.92   63.67 1173.26   64.59 1185.63   68.22
 1198.72   68.72 1232.25   68.04 1383.53      68 1437.01   69.57 1558.87   70.23
 1619.23   71.62 2017.83   73.97 2130.37   75.41 2174.44   74.99 2314.44   77.12
#Mann= 4 ,-1 , 0
       0     .99       0   476.4     .11       0 1131.76     .06       0
 1185.63      .1       0
Bank Sta=1131.76,1185.63
XS Rating Curve= 0
Exp/Cntr=.5,.3

Type RM Length L Ch R = 1 ,11259.25,52.4,52.45,52.95
BEGIN DESCRIPTION:
Xs 3/4;
Channel geometry adjusted for slope and width
xs shifted 42.77' to the right to allow encroachment setting
END DESCRIPTION:
XS GIS Cut Line= 5
      3157203.49    13929736.765     3157337.225    13929616.412
     3157763.099    13929200.024     3157794.988     13928532.24
     3157827.113    13927642.029
#Sta/Elev= 30
   42.77   72.75   180.6      72  216.43   70.75  246.94   71.82  290.02   71.89
  388.58      70  457.85   70.57  514.25      70  562.74   68.28  606.36   68.86
  680.05      68  805.54   68.14  940.54   66.82 1021.38   67.67 1092.05   66.47
  1152.9   66.51 1158.34   68.28 1200.86   67.93 1224.37   58.25 1229.63   58.46
 1235.02   63.36 1242.36   64.28 1254.73   67.91 1435.93   67.78 1450.15   68.86
 1507.21   70.01 1659.23   70.74 1716.68   71.94 2305.54   76.37 2377.63   76.27
#Mann= 4 ,-1 , 0
   42.77     .99       0  457.85     .11       0 1200.86     .06       0
 1254.73      .1       0
#XS Ineff= 2 , 0
   42.77 1200.86   67.75 1254.73   42.77   67.75
Permanent Ineff=
       F       F
Bank Sta=1200.86,1254.73
XS Rating Curve= 0
Exp/Cntr=.5,.3

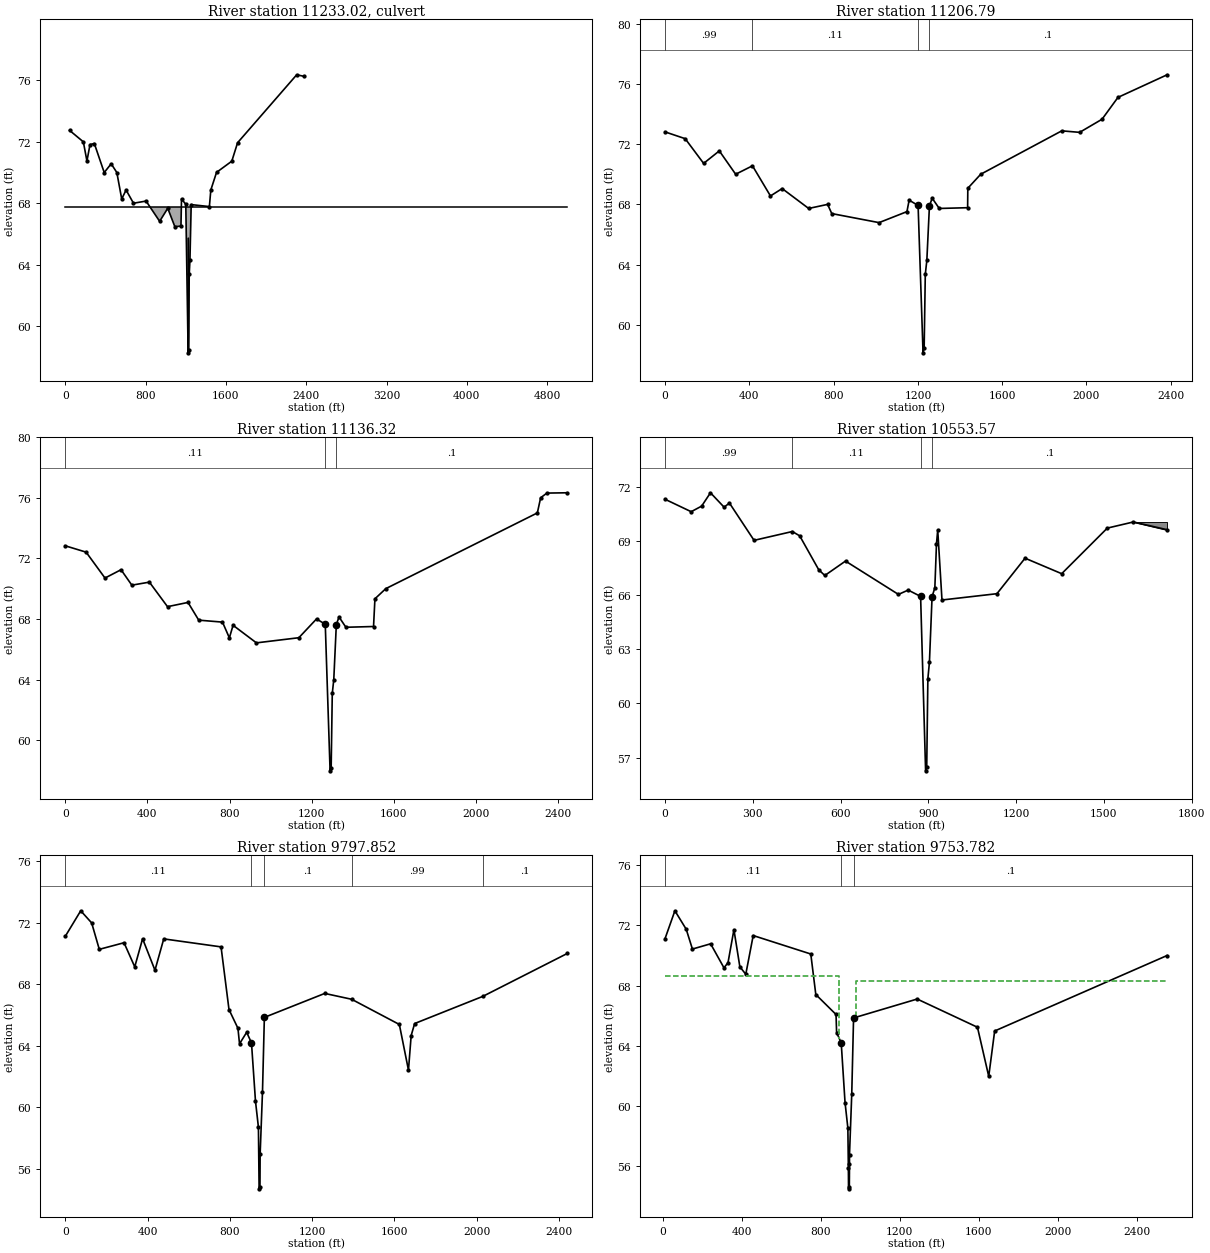
Type RM Length L Ch R = 2 ,11233.02,,,
BEGIN DESCRIPTION:
(424s6)   Private Road
New Culvert added to geometry per PMT request
END DESCRIPTION:
Bridge Culvert--1,0,-1,-1, 0
Deck Dist Width WeirC Skew NumUp NumDn MinLoCord MaxHiCord MaxSubmerge Is_Ogee
18.225,16,2.6,0, 2, 2, , , .95, 0, 0,0,,
       0    5000
   67.75   67.75
                
       0    5000
   67.75   67.75
                
BR Coef=-1 , 0 , 0 ,, 0 ,,,.8,0,,0,
WSPro=,,,, 1 ,,,, 0 ,,,, 0 ,,,,-1 ,-1 ,-1 , 0 , 0 , 0 , 0 , 0
Culvert=1,7.5,,30,.015,.5,1,55,1,58.25,1226.8,58.25,1226.8,Culvert #1  , 0 ,11.225
Culvert Bottom n=.015
BC Design=,, 0 ,, 0 ,,,,,,

Type RM Length L Ch R = 1 ,11206.79,77.22,70.48,72.84
BEGIN DESCRIPTION:
XS 2/4;
Channel geometry adjusted for slope and width
END DESCRIPTION:
XS GIS Cut Line= 6
      3157205.77    13929744.372     3157343.655    13929638.871
     3157808.119    13929231.913     3157821.249    13929061.215
      3157847.51    13928530.365     3157876.578    13927642.029
#Sta/Elev= 30
       0   72.81   95.52   72.36     183   70.72  257.47   71.55  335.06      70
  414.82   70.56   500.2   68.56  555.68   69.05  681.56   67.73  771.45      68
  791.14   67.39 1015.62   66.79 1147.94   67.52 1158.34   68.28 1200.86   67.93
 1224.37   58.15 1229.63   58.46 1235.02   63.36 1242.36   64.28 1254.73   67.91
 1267.82   68.41 1301.35   67.73 1435.93   67.78 1436.86   69.07 1498.04      70
 1882.74   72.88 1967.61   72.78 2073.86   73.65 2149.44    75.1 2382.65    76.6
#Mann= 4 ,-1 , 0
       0     .99       0  414.82     .11       0 1200.86     .06       0
 1254.73      .1       0
#XS Ineff= 2 , 0
       0 1200.86   67.75 1254.73       0   67.75
Permanent Ineff=
       F       F
Bank Sta=1200.86,1254.73
XS Rating Curve= 0
Exp/Cntr=.5,.3

Type RM Length L Ch R = 1 ,11136.32,285.33,582.74,660.17
BEGIN DESCRIPTION:
XS 1/4;
Channel geometry adjusted for slope and width
END DESCRIPTION:
XS GIS Cut Line= 5
      3157205.01    13929754.261     3157307.705    13929677.432
     3157393.737    13929616.682     3157872.082     13929274.38
     3157980.006    13927655.519
#Sta/Elev= 30
       0   72.83  101.81   72.41  193.72    70.7  271.77   71.25  324.43   70.23
  409.89   70.43  498.08   68.81  597.87   69.09  650.06   67.92  765.78   67.79
  799.25   66.75  817.32   67.58  930.94   66.42  1137.6   66.76 1223.59      68
 1266.11   67.65 1289.62   57.97 1294.88   58.18 1300.27   63.08 1307.61      64
 1319.98   67.63 1333.07   68.13  1366.6   67.45 1501.18    67.5 1507.94   69.33
 1560.81      70 2298.68      75  2314.7      76 2345.26   76.31 2444.23   76.33
#Mann= 3 , 0 , 0
       0     .11       0 1266.11     .06       0 1319.98      .1       0
Bank Sta=1266.11,1319.98
XS Rating Curve= 0
Exp/Cntr=.3,.1

Type RM Length L Ch R = 1 ,10553.57,630.38,755.73,775.19
BEGIN DESCRIPTION:
424v2
Bank Station offset =      4109
The high point on the ROB is local and is a very small high area, as seen from the TIN. The mrSids do not show any areas of concern. The area on the ROB is not ineffective.
END DESCRIPTION:
XS GIS Cut Line= 4
     3157318.927    13929675.304     3157964.562    13929337.641
     3158245.573    13929205.964     3158849.265     13928899.33
#Sta/Elev= 30
       0   71.33   89.27   70.64  125.01   70.95  155.21   71.69  201.81   70.89
  220.04   71.12  304.22   69.05  435.05   69.54  460.18    69.3  525.22   67.42
  546.03    67.1  616.77    67.9  797.72   66.05  830.94   66.29  873.46   65.94
  890.56   56.26  894.38   56.47   898.3   61.37  903.64   62.29  912.64   65.92
  922.16   66.42  927.77   68.87     932   69.62  946.54   65.74 1134.39   66.09
  1230.5   68.06 1355.72    67.2 1511.65   69.73 1600.79   70.07 1716.04   69.64
#Mann= 4 ,-1 , 0
       0     .99       0  435.05     .11       0  873.46     .06       0
  912.64      .1       0
#Block Obstruct= 1 ,-1
 1600.79 1716.04   70.07
Bank Sta=873.46,912.64
XS Rating Curve= 0
Exp/Cntr=.3,.1

Type RM Length L Ch R = 1 ,9797.852,29.82,44.07,42.42
BEGIN DESCRIPTION:
424s3u.  Surveyed section.  XS 4/4.
Bank Station offset =      4058
Adjusted expansion and contraction coefficients.
END DESCRIPTION:
XS GIS Cut Line= 5
     3157432.737    13929869.755     3158320.435    13929930.777
     3158422.115    13929919.628     3159459.416     13929888.59
 3159869.232704813929876.3275122
#Sta/Elev= 30
       0   71.11    75.4   72.78  128.61   71.99  165.62   70.27   285.9    70.7
  337.97   69.13  376.11   70.96  436.25   68.91  478.89   70.95  757.41   70.43
  796.01   66.35  839.47   65.13  847.17   64.12  881.92   64.87  905.31   64.18
   924.7   60.39  939.01   58.69  942.39   54.68  946.46   54.77   947.3   56.92
  958.74   60.97   967.9   65.84 1261.35    67.4 1392.03   67.02  1623.9   65.38
 1668.23   62.41 1681.35   64.66 1698.25   65.44 2029.85   67.21 2439.85      70
#Mann= 5 ,-1 , 0
       0     .11       0  905.31     .06       0   967.9      .1       0
 1392.03     .99       0 2029.85      .1       0
Bank Sta=905.31,967.9
XS Rating Curve= 0
Exp/Cntr=.5,.3

Type RM Length L Ch R = 1 ,9753.782,125.73,111.88,127.42
BEGIN DESCRIPTION:
Copy of 424s3u.   XS 3/4.
Bank Station offset =      4070
Adjusted elevations inside the channel banks based on the slope calculated between RS 9797 and RS 8480.
Adjusted expansion and contraction coefficients.
Overbank reach lengths are greater than the channel reach length due to narrowing of the floodplain as it approaches a structure.
END DESCRIPTION:
XS GIS Cut Line= 6
     3157459.642    13929905.246     3158346.979    13929960.386
     3158354.993    13929960.386     3158449.447    13929959.241
     3159486.321    13929924.082 3160001.454867113929906.6145048
#Sta/Elev= 30
   10.33   71.13   60.13   72.98   117.5   71.75  148.92   70.43  241.16   70.78
  308.84   69.18  329.27   69.52  359.32   71.72  389.38   69.25  419.44   68.75
  456.99   71.33  748.86    70.1  774.32    67.4  876.87   66.07   879.7   64.87
  903.09   64.18  922.48  60.204  936.79  58.504  939.37  55.854  940.17  54.454
  944.24  54.584  945.02  56.094  945.08  56.734  956.52  60.784  965.68   65.84
  1288.1    67.1 1593.58   65.22 1650.74   61.95 1680.76   64.97 2554.75      70
#Mann= 3 , 0 , 0
   10.33     .11       0  903.09     .06       0  965.68      .1       0
#XS Ineff= 2 , 0
   10.33  894.33   68.64  977.33   10.33   68.32
Permanent Ineff=
       F       F
Bank Sta=903.09,965.68
XS Rating Curve= 0
Exp/Cntr=.5,.3

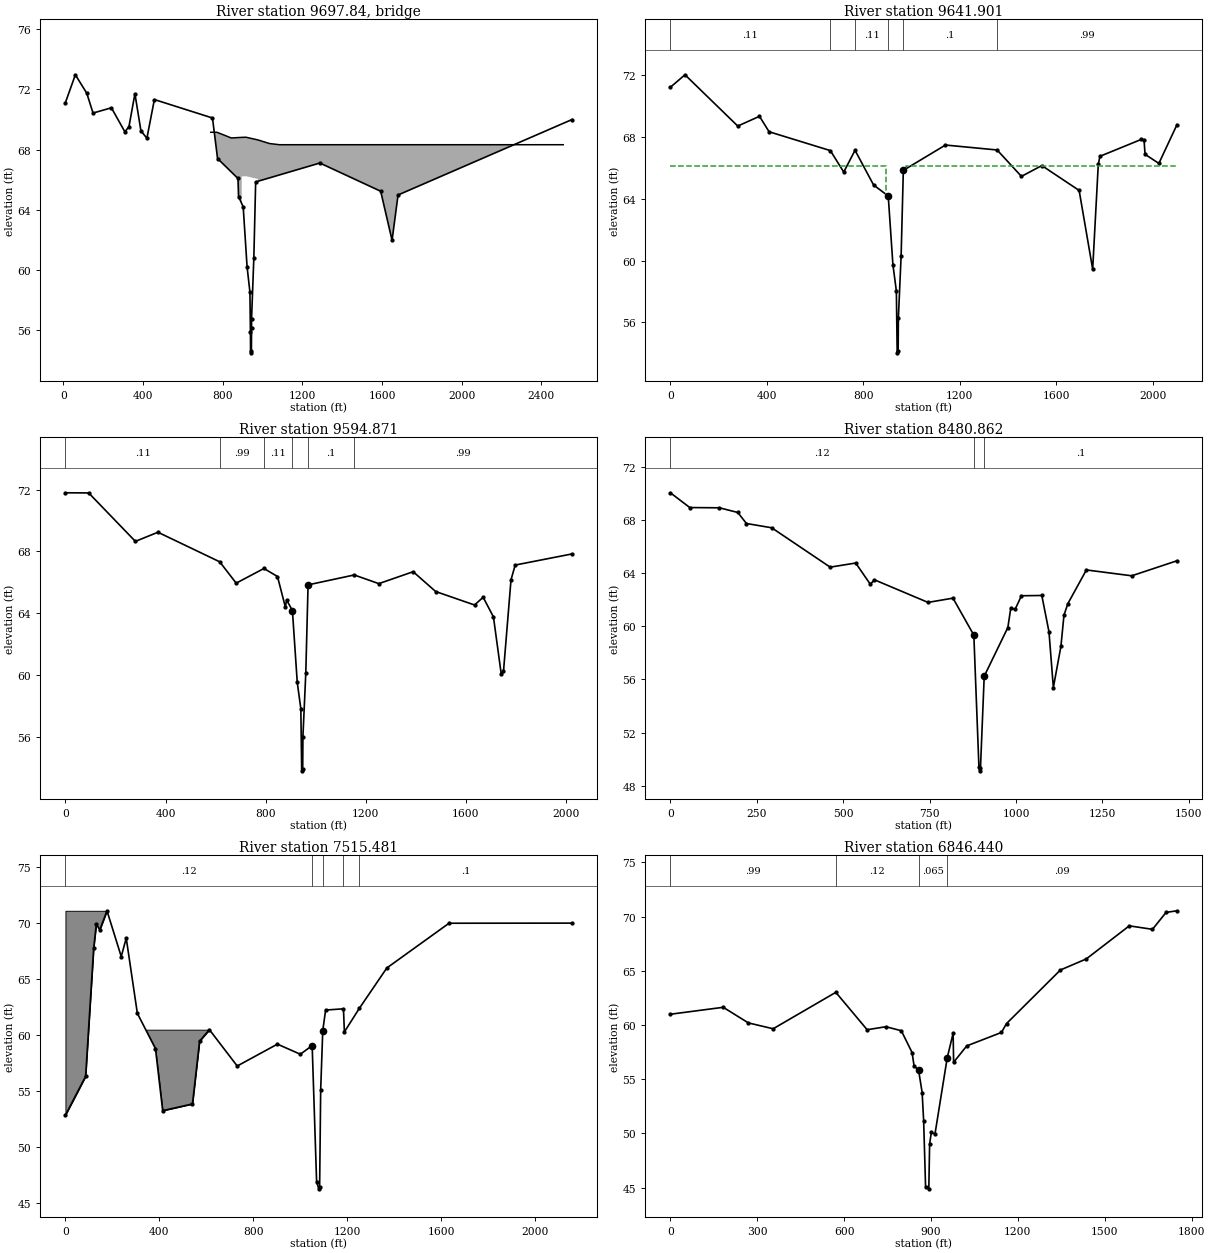
Type RM Length L Ch R = 3 ,9697.84 ,,,
BEGIN DESCRIPTION:
(424s3)      Farm Market 1960
END DESCRIPTION:
Bridge Culvert--1,0,-1,-1, 0
Deck Dist Width WeirC Skew NumUp NumDn MinLoCord MaxHiCord MaxSubmerge Is_Ogee
17.392,77.1,2.6,0, 11, 11, 68.32, , .95, 0, 0,0,,
  740.33  771.22  843.15  895.57  895.57  916.98  976.79  976.79 1034.91 1085.22
 2510.33
   69.15   69.15   68.77   68.81   68.81   68.82   68.64   68.64    68.4   68.32
   68.32
                                   66.21   66.22   66.04
        
     370  770.89  842.82  895.24  895.24  916.65  976.46  976.46 1034.58 1084.89
    2090
   69.15   69.15   68.77   68.81   68.81   68.82   68.64   68.64    68.4   68.32
   68.32
                                   66.21   66.22   66.04
        
BR Coef=-1 , 0 , 0 ,, 0 ,,,.8,0,,0,
WSPro=,,,, 1 ,,,, 0 ,,,, 0 ,,,,-1 ,-1 ,-1 , 0 , 0 , 0 , 0 , 0
BC Design=,, 0 ,, 0 ,,,,,,

Type RM Length L Ch R = 1 ,9641.901,47.9,47.03,50.06
BEGIN DESCRIPTION:
Copy of 424s3u.   XS 2/4.
Bank Station offset =      4060
Adjusted elevations inside the channel banks based on the slope calculated between RS 9797 and RS 8480.
Adjusted expansion and contraction coefficients.
cross section extended on ROB
END DESCRIPTION:
XS GIS Cut Line= 6
     3157468.708    13930093.593     3158347.589    13930070.823
     3158355.603    13930070.823     3158450.057    13930069.679
     3159464.582    13930119.778 3159551.575451213930065.4066259
#Sta/Elev= 30
       0   71.22   60.66   72.03  279.35   68.71  369.38   69.34  409.26   68.34
   663.1   67.12  718.73   65.73  765.48   67.14  842.49   64.89  903.09   64.18
  922.48  59.733  936.79  58.033  940.17  54.023  944.24  54.113  945.08  56.263
  956.52  60.313  965.68   65.84 1140.32   67.48  1354.4   67.16 1455.25   65.45
 1539.79   66.15 1694.41   64.54 1750.49   59.44 1773.71   66.22 1780.53   66.75
 1951.33   67.84  1963.4   67.81 1967.59   66.88 2024.86   66.29    2100    68.8
#Mann= 6 ,-1 , 0
       0     .11       0   663.1     .99       0  765.48     .11       0
  903.09     .06       0  965.68      .1       0  1354.4     .99       0
#XS Ineff= 2 , 0
       0     895    66.1     977       0    66.1
Permanent Ineff=
       F       F
Bank Sta=903.09,965.68
XS Rating Curve= 0
Exp/Cntr=.5,.3

Type RM Length L Ch R = 1 ,9594.871,1045.69,1114.01,887.19
BEGIN DESCRIPTION:
Copy of 424s3u.   XS 1/4.
Bank Station offset =      4056
Adjusted elevations inside the channel banks based on the slope calculated between RS 9797 and RS 8480.
END DESCRIPTION:
XS GIS Cut Line= 6
     3157468.437    13930140.592     3158347.318    13930117.823
     3158355.333    13930117.823     3158449.786    13930116.678
     3159464.311    13930166.777     3159487.586     13930152.23
#Sta/Elev= 30
       0   71.79    92.9   71.78  279.62   68.65  369.65   69.24  616.59   67.33
  682.47   65.95  793.42    66.9  847.52   66.38  879.18   64.39  883.75   64.87
  907.14   64.18  926.53  59.535  940.84  57.835  944.22  53.825  948.29  53.915
  949.13  56.025  960.57  60.115  969.73   65.84 1154.17   66.48  1252.5   65.92
 1389.73   66.69 1479.66   65.41 1635.07   64.54 1669.47   65.04 1710.63   63.77
 1741.96   60.05 1750.77   60.25  1780.8   66.17 1797.58   67.12 2024.86   67.84
#Mann= 6 ,-1 , 0
       0     .11       0  616.59     .99       0  793.42     .11       0
  907.14     .06       0  969.73      .1       0 1154.17     .99       0
Bank Sta=907.14,969.73
XS Rating Curve= 0
Exp/Cntr=.3,.1

Type RM Length L Ch R = 1 ,8480.862,871.87,965.38,849.22
BEGIN DESCRIPTION:
424v3
Bank Station offset =      4106
END DESCRIPTION:
XS GIS Cut Line= 4
     3158109.242    13931043.322     3158959.837    13930841.033
     3158991.956    13930834.442     3159536.948     13930711.82
#Sta/Elev= 30
       0   70.03   56.25   68.92  142.09    68.9  195.13   68.55   220.1   67.72
  293.14    67.4  462.36   64.44  536.22   64.75  578.59   63.15  590.23   63.49
   745.4   61.79  817.64   62.11  877.97   59.33  892.68   49.44  894.47   49.13
  897.12   49.31  907.98   56.24  976.36    59.9  985.02   61.39  997.18   61.26
 1015.76   62.29 1074.64   62.31 1095.37   59.58 1108.01   55.39 1129.92   58.49
 1138.76   60.83 1149.86   61.69 1203.56   64.23 1334.81   63.79 1465.72   64.92
#Mann= 3 , 0 , 0
       0     .12       0  877.97    .065       0  907.98      .1       0
Bank Sta=877.97,907.98
XS Rating Curve= 0
Exp/Cntr=.3,.1

Type RM Length L Ch R = 1 ,7515.481,780.98,669.04,513.41
BEGIN DESCRIPTION:
424v4
Bank Station offset =      3922
Blocks in LOB based on ponds/pits not part of the main conveyance area
END DESCRIPTION:
XS GIS Cut Line= 5
     3158037.962    13931851.205     3159061.602    13931702.065
     3159137.448    13931691.163     3159255.044    13931596.682
     3159838.717    13930918.973
#Sta/Elev= 30
       0   52.86    85.9   56.32  120.18   67.75  131.37   69.88  146.19   69.38
  176.85   71.08  237.48      67   258.8   68.64  306.06   61.94  383.09   58.79
   413.9   53.26  540.65   53.86  570.97   59.46  612.71   60.48  731.14   57.24
  902.21   59.19  999.79   58.29 1050.13   59.06 1068.98   46.94 1078.01   46.29
 1081.89   46.46 1086.37   55.12  1095.2   60.39 1107.34   62.23 1183.38   62.34
 1187.23   60.28 1250.49   62.37 1367.88   65.98 1632.65   69.97 2156.33   69.98
#Mann= 5 ,-1 , 0
       0     .12       0 1050.13    .065       0  1095.2      .1       0
 1183.38     .99       0 1250.49      .1       0
#Block Obstruct= 2 ,-1
       0  176.85   71.08     265  612.71   60.48
Bank Sta=1050.13,1095.2
XS Rating Curve= 0
Exp/Cntr=.3,.1

Type RM Length L Ch R = 1 ,6846.440,30.05,31,11.53
BEGIN DESCRIPTION:
424s4u.  Surveyed section.  XS 4/4.
Bank Station offset =      4108
Adjusted expansion and contraction coefficients.
END DESCRIPTION:
XS GIS Cut Line= 6
     3159104.466    13932886.575      3159462.88    13932199.649
     3159553.417     13932035.84     3159554.582    13932006.153
     3159497.785    13931424.554     3159592.084    13931279.068
#Sta/Elev= 30
       0   60.99  182.57   61.63  269.44   60.19  354.97   59.65  571.32   63.01
  679.55   59.56  744.41   59.84  797.45   59.47  834.67   57.46  841.48   56.24
  857.22   55.82  869.41   53.77   874.6   51.18  881.29   45.06  892.45   44.89
  895.25   49.04  901.17   50.09  913.73   49.94  955.95   56.96   976.4   59.24
  978.14   56.56 1023.44   58.07 1143.18   59.31 1160.83   60.13 1346.91   65.07
 1436.23   66.09 1584.68   69.14 1664.77   68.82 1711.75   70.38 1749.42   70.53
#Mann= 4 ,-1 , 0
       0     .99       0  571.32     .12       0  857.22    .065       0
  955.95     .09       0
Bank Sta=857.22,955.95
XS Rating Curve= 0
Exp/Cntr=.5,.3

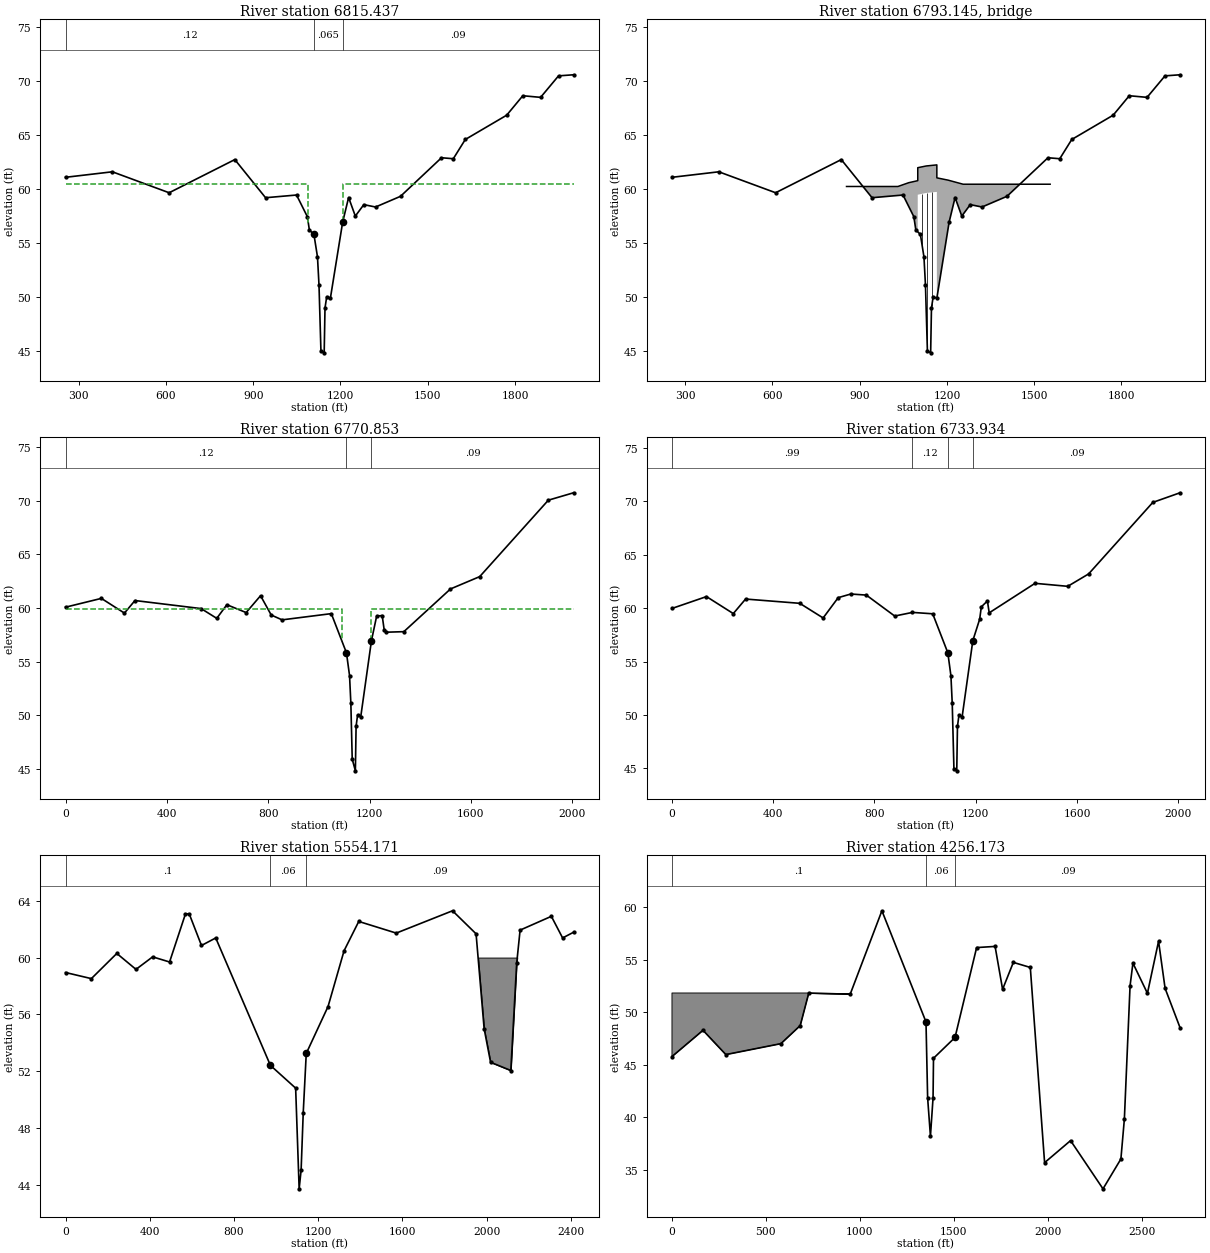
Type RM Length L Ch R = 1 ,6815.437,110.99,44.58,53.91
BEGIN DESCRIPTION:
Copy of 424s4u.   XS 3/4.
Bank Station offset =      4111
Adjusted elevations inside the channel banks based on the slope calculated between RS 6846 and RS 5554.
Adjusted expansion and contraction coefficients.
Overbank reach lengths are greater than the channel reach length due to narrowing of the floodplain as it approaches a structure.
END DESCRIPTION:
XS GIS Cut Line= 6
     3159130.998    13932900.576     3159548.907    13932108.296
     3159557.734    13932065.421     3159562.148    13931984.085
     3159519.208    13931437.085     3159607.912    13931284.344
#Sta/Elev= 30
  254.71   61.11  415.72   61.62     611   59.68  836.75   62.75  942.46   59.22
 1048.95   59.47 1086.17   57.46 1092.98   56.24 1108.72   55.82 1120.91  53.742
  1126.1  51.152 1132.79  45.032 1143.95  44.862 1146.75  49.012 1152.67  50.062
 1165.23  49.912 1207.45   56.96  1227.9   59.24 1251.01   57.52 1280.16   58.58
 1320.52   58.36 1406.32   59.35 1547.23   62.92 1587.83   62.83    1629   64.61
 1771.35   66.86 1826.75   68.66 1887.89   68.51 1949.57    70.5 2001.16    70.6
#Mann= 3 , 0 , 0
  254.71     .12       0 1108.72    .065       0 1207.45     .09       0
#XS Ineff= 2 , 0
       0 1089.71   60.47 1207.45       0   60.47
Permanent Ineff=
       F       F
Bank Sta=1108.72,1207.45
XS Rating Curve= 0
Exp/Cntr=.5,.3

Type RM Length L Ch R = 3 ,6793.145,,,
BEGIN DESCRIPTION:
Sherwell Road  (424s4)    Wooden Bridge
Adjusted station offsets by hand to get the structure to line up in the channel. Try to base correct position of structure by looking at pictures.
END DESCRIPTION:
Bridge Culvert--1,0,-1,-1, 0
Deck Dist Width WeirC Skew NumUp NumDn MinLoCord MaxHiCord MaxSubmerge Is_Ogee
12.29,20,2.6,0, 11, 11, 60.26, , .95, 0, 0,0,,
  854.71 1031.42 1068.47 1099.61 1099.61 1128.85 1165.27 1165.27 1203.58 1255.56
 1554.71
   60.26   60.26   60.61    60.8      62   62.16   62.26   61.06   60.85   60.47
   60.47
       0       0       0       0    59.5   59.66   59.76       0       0       0
       0
     760 1031.71 1068.76  1099.9  1099.9 1129.14 1165.56 1165.56 1203.87 1255.85
    1600
   60.26   60.26   60.61    60.8      62   62.16   62.26   61.06   60.85   60.47
   60.47
       0       0       0       0    59.5   59.66   59.76       0       0       0
       0
Pier Skew, UpSta & Num, DnSta & Num=  ,1115.14, 2 ,1115.14, 2 , 0 , 0 , 0 ,,
       1       1
       0      60
       1       1
       0      60
Pier Skew, UpSta & Num, DnSta & Num=  ,1131.88, 2 ,1131.88, 2 , 0 , 0 , 0 ,,
       1       1
       0      60
       1       1
       0      60
Pier Skew, UpSta & Num, DnSta & Num=  ,1147.98, 2 ,1147.98, 2 , 0 , 0 , 0 ,,
       1       1
       0      60
       1       1
       0      60
BR Coef=-1 , 0 , 0 ,, 0 ,,,.8,-1,,0,
WSPro=,,,, 1 ,,,, 0 ,,,, 0 ,,,,-1 ,-1 ,-1 , 0 , 0 , 0 , 0 , 0
BC Design=,, 0 ,, 0 ,,,,,,

Type RM Length L Ch R = 1 ,6770.853,35.22,36.92,30.52
BEGIN DESCRIPTION:
Copy of 424s4u.   XS 2/4.
Bank Station offset =      3856
Adjusted elevations inside the channel banks based on the slope calculated between RS 6864 and RS 5554.
Adjusted expansion and contraction coefficients.
END DESCRIPTION:
XS GIS Cut Line= 6
     3159440.634    13933278.958     3159532.553    13932403.845
     3159562.208    13932258.535     3159617.071    13931951.603
     3159609.657    13931591.292     3159655.622    13931290.291
#Sta/Elev= 30
       0   60.07  141.48   60.89  232.48   59.52  274.18   60.69   535.2   59.94
  596.92   59.03  636.73    60.3  712.92   59.57  769.75   61.14  811.84   59.34
  854.75   58.89 1048.95   59.47 1108.72   55.82 1120.91  53.703  1126.1  51.113
 1131.51  45.913 1143.95  44.823 1146.75  48.973 1152.67  50.023 1165.23  49.873
 1207.45   56.96  1227.9   59.24  1249.7   59.29 1257.47   57.99 1266.29   57.74
 1335.23   57.79 1519.31   61.77 1634.68   62.92  1905.4   70.04 2004.93   70.73
#Mann= 3 , 0 , 0
       0     .12       0 1108.72    .065       0 1207.45     .09       0
#XS Ineff= 2 , 0
       0    1090    59.9 1207.45       0    59.9
Permanent Ineff=
       F       F
Bank Sta=1108.72,1207.45
XS Rating Curve= 0
Exp/Cntr=.5,.3

Type RM Length L Ch R = 1 ,6733.934,957.06,1179.76,1287.86
BEGIN DESCRIPTION:
Copy of 424s4u.   XS 1/4.
Bank Station offset =      3875
Adjusted elevations inside the channel banks based on the slope calculated between RS 6864 and RS 5554.
END DESCRIPTION:
XS GIS Cut Line= 6
     3159470.372    13933282.911     3159562.292    13932407.798
     3159591.947    13932262.488     3159646.809    13931955.556
     3159639.606    13931593.038     3159685.572    13931292.037
#Sta/Elev= 30
       0   59.97  136.28   61.08  242.26   59.49  290.82   60.85  504.83   60.45
  597.16   59.08  656.71   60.98  706.55   61.32  767.79   61.22  879.93   59.26
  950.15    59.6 1030.11   59.47 1089.88   55.82 1102.07   53.67 1107.26   51.08
 1113.95   44.96 1125.11   44.78 1127.91   48.94 1133.83   49.99 1146.39   49.84
 1188.61   56.96 1215.72   58.97 1222.15   60.12 1246.23   60.67 1253.31   59.56
 1434.32   62.32 1563.62   62.04 1646.08    63.2 1899.69   69.89 2007.14   70.79
#Mann= 4 ,-1 , 0
       0     .99       0  950.15     .12       0 1089.88    .065       0
 1188.61     .09       0
Bank Sta=1089.88,1188.61
XS Rating Curve= 0
Exp/Cntr=.3,.1

Type RM Length L Ch R = 1 ,5554.171,1316.4,1298,1094.88
BEGIN DESCRIPTION:
424v5
Bank Station offset =      3891
Block in ROB is pond area, not available for storage.
END DESCRIPTION:
XS GIS Cut Line= 4
     3159491.841    13933901.208     3159937.373    13933203.259
       3160274.3    13933073.586     3161413.227    13932627.034
#Sta/Elev= 30
       0   58.95  122.76   58.52   243.6   60.29  334.67   59.17  413.69   60.05
  494.13   59.69  569.34   63.06   587.3   63.08  645.65   60.85  713.36   61.38
     973   52.42 1092.81   50.82 1109.45   43.74 1118.77   45.05 1128.85    49.1
 1143.19   53.26 1246.69   56.56 1322.75   60.48 1392.47   62.54 1570.56   61.72
 1837.68   63.29 1949.55   61.67 1987.83      55 2018.42   52.64 2114.53   52.06
 2142.39    59.6 2158.57   61.93 2307.03    62.9 2360.47   61.38 2412.39   61.78
#Mann= 3 , 0 , 0
       0      .1       0     973     .06       0 1143.19     .09       0
#Block Obstruct= 1 ,-1
    1850    2280      60
Bank Sta=973,1143.19
XS Rating Curve= 0
Exp/Cntr=.3,.1

Type RM Length L Ch R = 1 ,4256.173,1357.91,1959.96,1540.54
BEGIN DESCRIPTION:
424v6
Bank Station offset =      3624
Added blocked and ineffective flows on ROB due to ponds.
On LOB, water will not be able to get inot this low area and hence this area will not be available for wither conyevance or storage. Hence a block is added.
END DESCRIPTION:
XS GIS Cut Line= 6
     3159228.828    13934602.295     3160395.505    13934435.354
     3160416.944    13934315.765     3160437.558    13934187.813
     3160448.962    13934118.919     3161640.892    13933939.159
#Sta/Elev= 30
       0   45.78  165.26   48.28  286.87   45.97  579.98   47.01  682.92   48.73
  728.44   51.83   948.8   51.71 1117.74   59.65 1352.45   49.08 1361.17   41.85
 1376.12   38.21 1390.06   41.86 1392.41   45.62    1507    47.6 1622.01   56.15
 1720.36   56.26 1760.29   52.18 1817.48   54.74 1907.83   54.26 1983.91   35.69
  2122.2   37.79 2294.89    33.2 2390.16   36.04 2408.66   39.84    2439   52.52
 2454.17   54.67 2531.42    51.8 2590.69   56.75 2625.48   52.27  2704.9   48.54
#Mann= 3 , 0 , 0
       0      .1       0 1352.45     .06       0    1507     .09       0
#Block Obstruct= 2 , 0
       0  943.65   51.83 1674.19       0   56.62
Bank Sta=1352.45,1507
XS Rating Curve= 0
Exp/Cntr=.3,.1

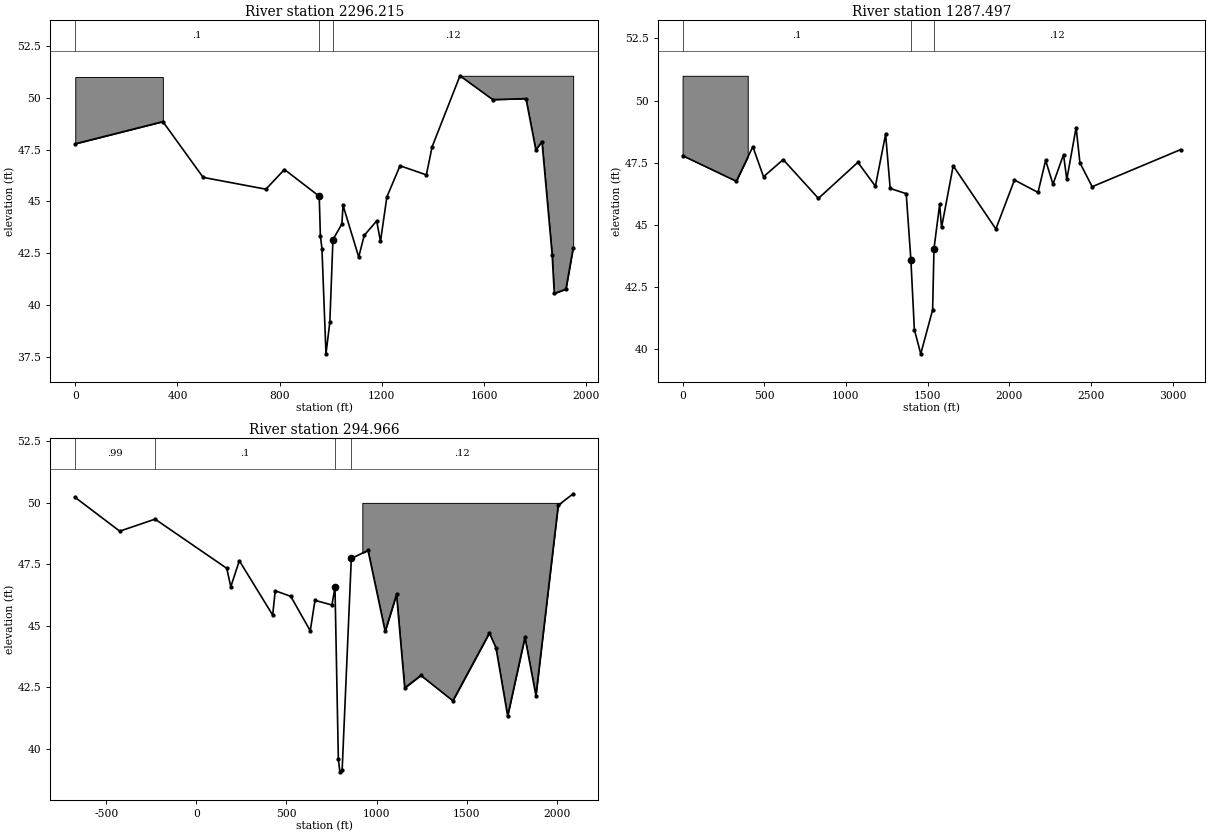
Type RM Length L Ch R = 1 ,2296.215,824.58,1008.72,983.9
BEGIN DESCRIPTION:
424v7
Bank Station offset =      4019
Blocked on LOB at watershed edge and ROB at low area that appears to be a borrow pit.
END DESCRIPTION:
XS GIS Cut Line= 4
     3159372.682    13935523.288     3160306.217    13935406.171
     3160333.885    13935319.874      3161192.26    13934996.214
#Sta/Elev= 30
       0   47.78  342.95   48.85  500.54   46.16  746.13   45.59  818.73   46.54
  954.93   45.25  959.46   43.34  965.55   42.73  981.33   37.65  996.49   39.19
  1008.6   43.16 1043.53   43.91 1048.13   44.81 1109.47   42.32 1130.95   43.36
 1179.83   44.06 1194.68   43.07 1219.73   45.22 1271.22   46.72 1374.27   46.28
 1396.59   47.63 1505.79   51.06 1634.26   49.91 1764.06   49.96 1802.65   47.49
 1826.69   47.89 1866.67   42.42 1874.79   40.56 1920.43   40.77 1948.84   42.76
#Mann= 3 , 0 , 0
       0      .1       0  954.93     .04       0  1008.6     .12       0
#Block Obstruct= 2 ,-1
 1505.79 1948.84   51.06       0  342.95      51
Bank Sta=954.93,1008.6
XS Rating Curve= 0
Exp/Cntr=.3,.1

Type RM Length L Ch R = 1 ,1287.497,1011.69,992.53,983.61
BEGIN DESCRIPTION:
424v8
Bank Station offset =      3542
Blocked at watershed edge on LOB and ROB.
END DESCRIPTION:
XS GIS Cut Line= 5
     3159381.826    13935868.361     3160760.314    13936061.337
     3160929.732    13936018.624     3161836.164    13935727.358
 3162341.010341613935565.1344967
#Sta/Elev= 30
       0   47.79  328.74   46.76   430.1   48.15  495.56   46.94  615.96   47.63
  831.66   46.07 1073.38   47.52 1180.52   46.56 1243.14   48.65 1271.15   46.47
 1369.28   46.26 1397.89    43.6 1419.22   40.79 1458.37   39.82 1531.06   41.59
 1539.38   44.05 1574.04   45.83 1585.77    44.9 1657.02   47.38  1918.2   44.84
 2032.24   46.81  2176.3   46.31 2223.02    47.6 2267.93   46.64  2332.6   47.83
 2352.56   46.83 2409.78   48.92 2432.99    47.5 2508.06   46.54    3049   48.03
#Mann= 3 , 0 , 0
       0      .1       0 1397.89     .04       0 1539.38     .12       0
#Block Obstruct= 2 , 0
       0   398.9      51    3021       0      51
Bank Sta=1397.89,1539.38
XS Rating Curve= 0
Exp/Cntr=.3,.1

Type RM Length L Ch R = 1 ,294.966 ,226.67,294.97,329.25
BEGIN DESCRIPTION:
424v9
Bank Station offset =      4188
Added block to keep water out of the WFSJ River channel or ponds and low areas adjacent to WFSJ River on ROB.  Water will not reach sufficient elevation to overtop ground on either side of main channel area based on LIDAR topography data.
END DESCRIPTION:
XS GIS Cut Line= 6
 3159472.030849513937449.7988001     3160094.939    13937197.669
     3160333.684    13937101.034     3160803.528    13936936.219
     3160933.443    13936889.582     3162070.825    13936514.605
#Sta/Elev= 30
    -672   50.22    -425   48.85    -229   49.34  168.84   47.34  191.07   46.59
  238.48   47.65  423.61   45.44  437.76   46.43  524.12    46.2  632.13    44.8
  658.26   46.04 752.382   45.85 769.343   46.57     788   39.59 796.479   39.07
 809.201   39.16  859.98   47.74  952.57   48.07 1047.76   44.78 1110.82   46.28
 1156.24   42.48 1245.83   42.99  1423.3   41.96 1626.01   44.71 1662.72   44.11
  1727.5   41.34  1823.5   44.54 1884.38   42.17 2008.02    49.9 2091.11   50.37
#Mann= 4 ,-1 , 0
    -672     .99       0    -229      .1       0 769.343     .04       0
  859.98     .12       0
#Block Obstruct= 2 ,-1
                             921    2100      50
Bank Sta=769.343,859.98
XS Rating Curve= 0
Exp/Cntr=.3,.1

Chan Stop Cuts=-1